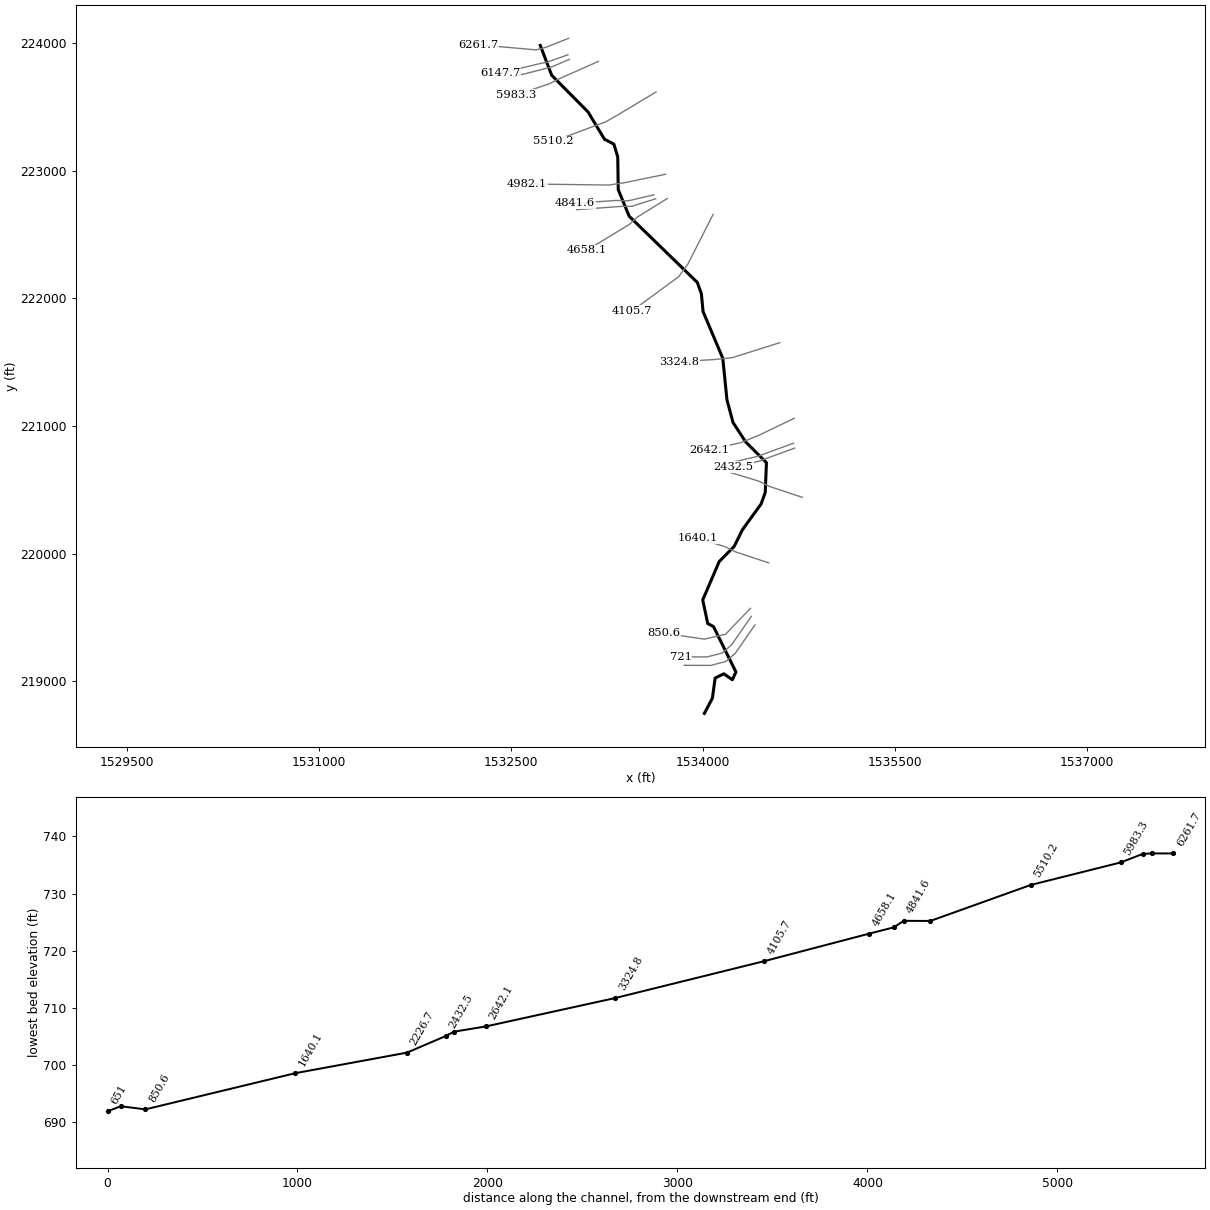
--- LNGRN.prj (project) ---

Proj Title=LNGRN
Current Plan=p01
Default Exp/Contr=0,0
English Units
Geom File=g01
Flow File=f01
Plan File=p01
BEGIN DESCRIPTION:
END DESCRIPTION:
DSS Export Rating Curves= 0
DSS Export Rating Curve Sorted= 0
DSS Export Volume Flow Curves= 0
DXF OffsetX= 0
DXF OffsetY= 0
DXF ScaleX= 0
DXF ScaleY= 0

--- LNGRN.p01 (plan) ---

Plan Title=Floodplain
Program Version=4.00
Geom File=g01
Flow File=f01
K Sum by GR=0
Std Step Tol=0.01
Critical Tol=0.01
Num of Std Step Trials=20
Max Error Tol=0.3
Flow Tol Ratio=0.001
Split Flow NTrial=30
Split Flow Tol=0.02
Split Flow Ratio=0.02
Log Output Level=0
Friction Slope Method=1
Unsteady Friction Slope Method=2
Unsteady Bridges Friction Slope Method=1
Global Log Level=0
CheckData=False
Run HTab=0
Run UNet=0
Run PostProcess=0
UNET Theta=0
UNET Theta Warmup=0
UNET ZTol=0
UNET ZSATol=0
UNET MxIter=0
UNET MaxInSteps=0
UNET DtIC=0
UNET DtMin=0
UNET MaxCRTS=0
UNET WFStab=0
UNET SFStab=0
UNET WFX=0
UNET SFX=0
UNET DSS MLevel=0
UNET DZMax Abort=0
UNET Convert EG Bridges=0
UNET Use Existing IB Tables=0
UNET Froude Limit=0
UNET Froude Power=0
Write IC File=0
Echo Input=False
Echo Output=False
Write Detailed=0

--- LNGRN.f01 (steady flow) ---

Flow Title=NFF Regression Equation
Program Version=4.10
Number of Profiles= 1
Profile Names=P100yr
River Rch & RM=LNGRN,Main            ,6261.7
937.6522
River Rch & RM=LNGRN,Main            ,5510.2
950.1054
River Rch & RM=LNGRN,Main            ,4105.7
1023.408
River Rch & RM=LNGRN,Main            ,3324.8
1130.032
River Rch & RM=LNGRN,Main            ,850.6
1161.624
Boundary for River Rch & Prof#=LNGRN,Main            , 1
Up Type= 0
Dn Type= 3
Dn Slope=0.0066
DSS Import GetInterval= 0
DSS Import GetPeak= 0
DSS Import FillOption= 0

--- LNGRN.g01 (geometry) ---

Geom Title=USGS 10m DEM
Program Version=4.10

River Reach=LNGRN           ,Main
Reach XY= 30
      1532730.88      223979.649     1532820.209      223745.915
     1533104.634      223458.439     1533232.224      223245.458
     1533305.889       223206.95     1533336.113        223107.2
     1533340.057       222850.47     1533425.437      222642.424
      1533957.48      222124.298     1533989.164      222037.493
     1534002.822      221895.869     1534156.785       221529.94
     1534189.381      221204.898     1534236.571      221028.039
     1534335.518      220875.397     1534497.826      220713.125
     1534488.373       220479.16     1534455.473      220388.609
     1534310.885      220189.002     1534245.837      220057.839
     1534128.748       219938.64     1534000.233      219638.588
     1534039.237      219453.197     1534083.818      219430.331
     1534259.627      219073.822     1534231.543      219013.485
     1534165.121      219060.138     1534097.119      219026.928
     1534075.769      218869.572     1534012.966      218750.229

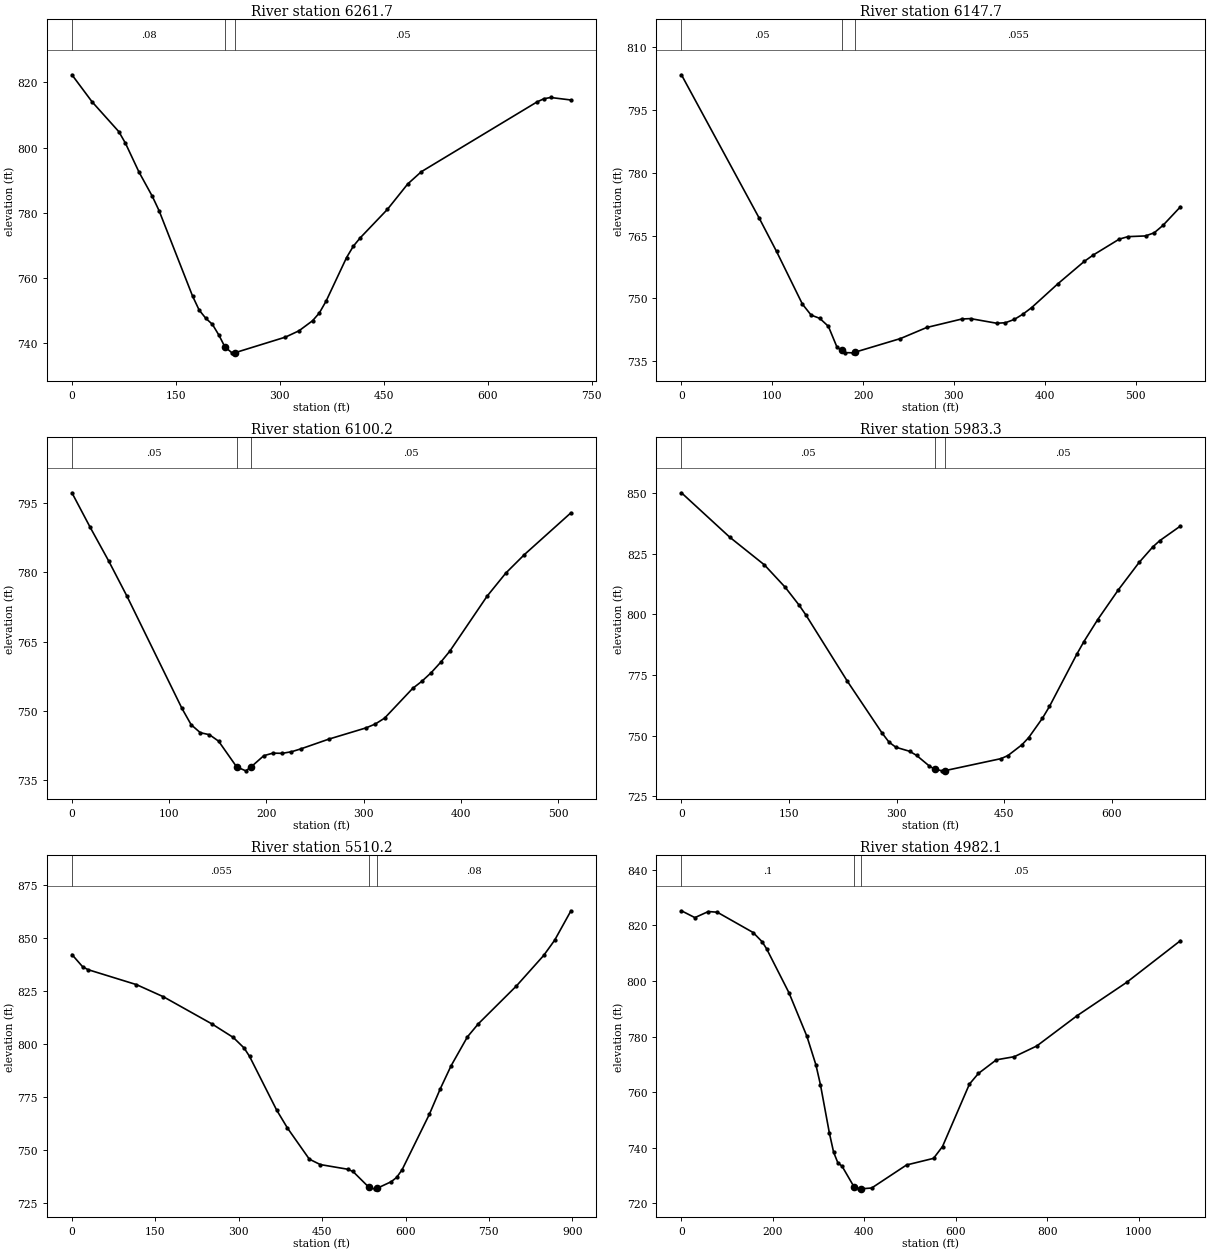
Type RM Length L Ch R = 1 ,6261.7  ,113.7,113.9,112.6
XS GIS Cut Line= 4
     1532951.737       224035.13     1532772.061        223963.8
     1532699.145      223944.703     1532249.492      223984.633
#Sta/Elev= 30
       0  822.36      29  814.08    67.7   804.9    77.3  801.32    96.7  792.53
     116  785.06   125.7  780.68     174  754.48   183.6  750.14   193.3  747.59
   202.7  745.77   212.2  742.41   220.8  738.81     231  737.02   235.8  737.09
     308  741.84   327.6  743.78   347.2  746.87     357  749.25   366.8  752.91
   396.3  766.26   406.1  769.76   415.9  772.29   455.2  781.04   484.6  788.86
   504.2  792.61     671  814.01   680.9  814.99   690.7  815.39   720.1  814.62
#Mann= 3 , 0 , 0
       0     .08       0   220.8    .045       0   235.8     .05       0
Bank Sta=220.8,235.8
XS Rating Curve= 0 ,0
Exp/Cntr=0.3,0.1

Type RM Length L Ch R = 1 ,6147.7  ,47.3,47.5,47.9
XS GIS Cut Line= 4
     1532947.409      223906.508      1532785.95      223849.217
     1532726.923      223837.064     1532417.895      223762.411
#Sta/Elev= 30
       0  803.39    85.7  769.15   104.7  761.24   133.2  748.66   142.8  746.04
   152.3  745.26   161.8  743.36   171.3  738.38   176.5   737.6   179.9  737.09
   188.5  737.03   191.5  737.21   241.2  740.44   270.1  743.08   308.7   745.1
   318.3   745.2   347.2  744.09   356.8  744.22   366.5     745   376.1  746.27
   385.7  747.84   414.6  753.53   443.5  758.84   453.2  760.34   482.1  764.17
   491.7  764.76     511  764.93   520.6  765.68   530.2  767.44   549.5  771.89
#Mann= 3 , 0 , 0
       0     .05       0   176.5     .04       0   191.5    .055       0
Bank Sta=176.5,191.5
XS Rating Curve= 0 ,0
Exp/Cntr=0.3,0.1

Type RM Length L Ch R = 1 ,6100.2  ,112.9,116.9,121.8
XS GIS Cut Line= 4
     1532957.825       223870.05     1532810.256       223807.55
     1532765.117      223797.133     1532468.242      223720.745
#Sta/Elev= 30
       0  797.28    18.8  789.77    37.7  782.52    56.6  774.83   113.1   750.5
   122.6  746.94     132  745.22   141.4  744.78   150.8  743.38   169.4  737.79
   178.8  736.94   184.4  737.83   197.3  740.23   206.6  740.78   216.2  740.74
   225.7  741.08   235.3   741.7   264.1  743.82   302.4  746.26     312  747.11
   321.5  748.38   350.3  754.82   359.9  756.39   369.4  758.24     379  760.46
   388.6  762.93   426.9  774.85   446.1  779.85   465.2  783.86   513.1  792.94
#Mann= 3 , 0 , 0
       0     .05       0   169.4     .04       0   184.4     .05       0
Bank Sta=169.4,184.4
XS Rating Curve= 0 ,0
Exp/Cntr=0.3,0.1

Type RM Length L Ch R = 1 ,5983.3  ,475.3,473.1,471.2
XS GIS Cut Line= 4
     1533185.444      223854.787     1532885.777      223721.613
     1532797.423      223677.704     1532542.215      223591.766
#Sta/Elev= 30
       0  850.06    67.5  831.72   115.7  820.34   144.7  811.11     164  803.78
   173.6  799.67   231.5  772.32   279.7  751.06   289.4   747.3     299  745.17
   318.3  743.49   327.9   741.8   345.9  737.38     353  736.14   363.8  735.44
     368  735.55   445.8  740.48   455.4  741.76   474.7  746.15   484.3  749.16
   503.5  757.16   513.2  761.97   551.6  783.66   561.2  788.69   580.5  797.79
   609.3  810.06   638.2  821.34   657.4  827.77     667  830.32   695.9  836.36
#Mann= 3 , 0 , 0
       0     .05       0     353     .04       0     368     .05       0
Bank Sta=353,368
XS Rating Curve= 0 ,0
Exp/Cntr=0.3,0.1

Type RM Length L Ch R = 1 ,5510.2  ,532.2,528.1,523.4
XS GIS Cut Line= 4
     1533635.965      223615.204     1533337.166      223436.022
     1533243.416      223382.203     1532830.221      223227.689
#Sta/Elev= 30
       0  842.24    19.4  836.41      29  835.08   116.1  828.01   164.5  822.28
   251.6  809.47   290.3  803.03   309.7  798.05   319.4  794.14   368.1  768.79
   387.7  760.22     427  745.53   446.7  742.97   495.7  740.78   505.5   739.7
   534.5  732.14   544.7   731.5   549.5  731.83   574.1  734.84     584  736.88
   593.8  740.49   642.8  766.67   662.4  778.69     682  789.66   711.4  803.33
     731   809.5   799.6  827.41   848.6  841.82   868.2  848.97   897.6  862.91
#Mann= 3 , 0 , 0
       0    .055       0   534.5    .045       0   549.5     .08       0
Bank Sta=534.5,549.5
XS Rating Curve= 0 ,0
Exp/Cntr=0.3,0.1

Type RM Length L Ch R = 1 ,4982.1  ,146.9,140.5,134.6
XS GIS Cut Line= 4
     1533711.052      222971.106     1533394.211      222906.002
     1533266.173      222886.471     1532628.152      222895.151
#Sta/Elev= 30
       0  825.27    29.4  822.81    58.8     825    78.4  824.75   156.8  817.44
   176.4  814.13   186.2  811.59   235.2  795.73   274.4  780.06     294  769.83
   303.9   762.7   323.5  745.25   332.7  738.39     342  734.57   351.2  733.34
   377.2  725.97   388.2   725.2   392.2   725.2     416   725.5   492.2  733.79
   551.2  736.17   570.8  740.42   629.7   762.9   649.3  766.72   688.6  771.63
   727.8  772.76   776.9  776.61   865.3  787.54   973.3  799.49  1091.1  814.52
#Mann= 3 , 0 , 0
       0      .1       0   377.2    .045       0   392.2     .05       0
Bank Sta=377.2,392.2
XS Rating Curve= 0 ,0
Exp/Cntr=0.3,0.1

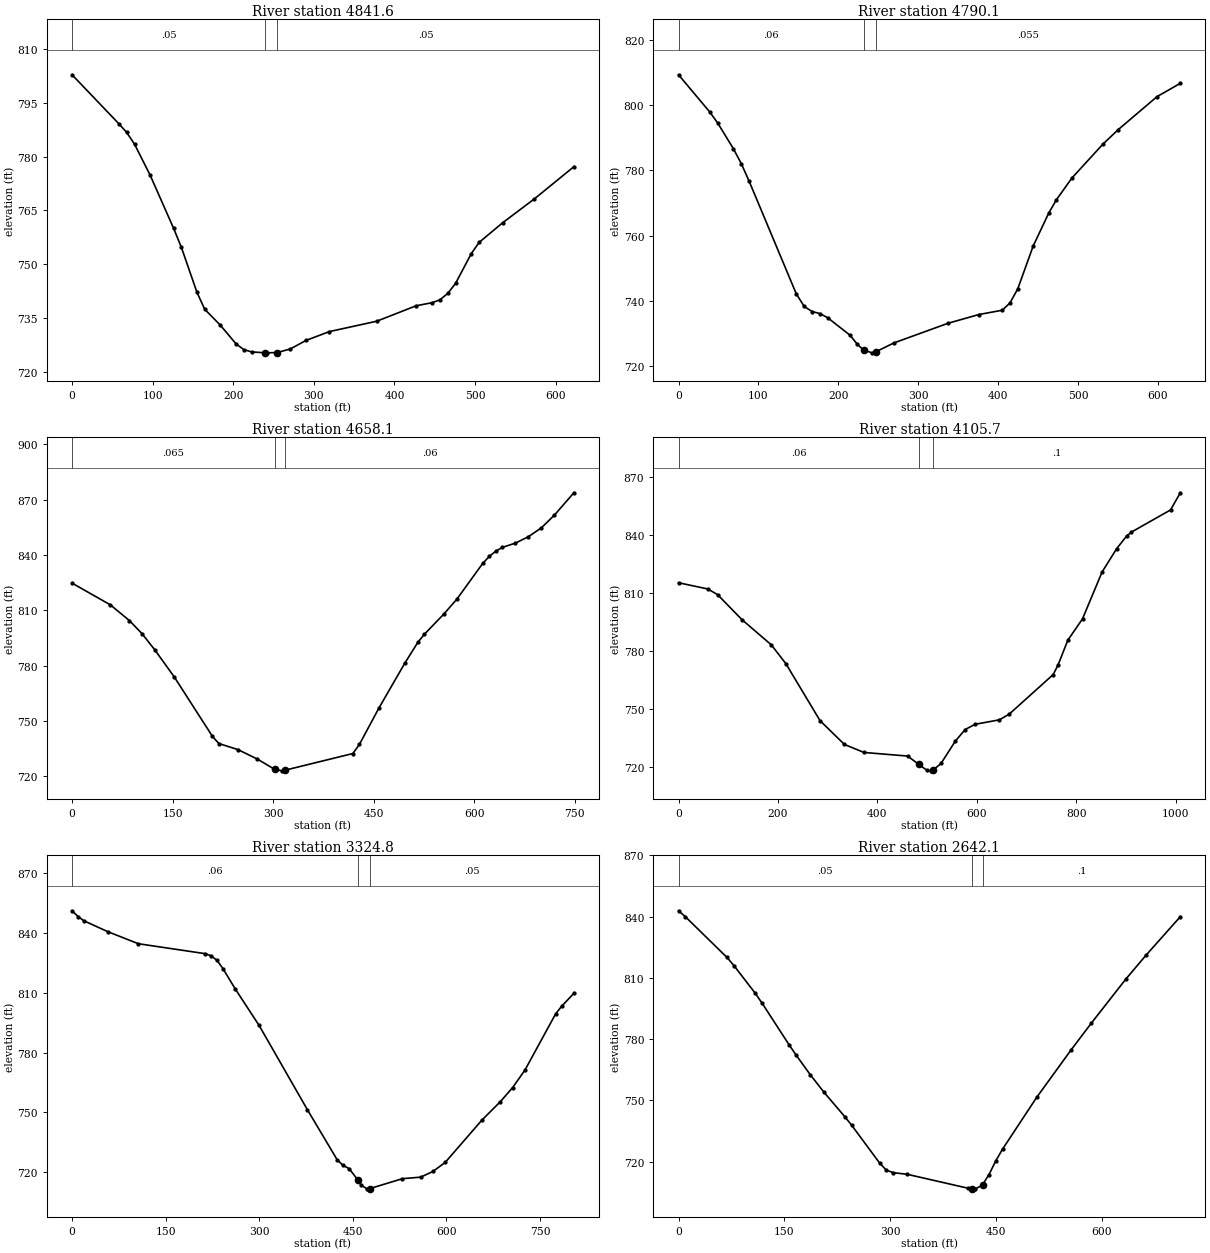
Type RM Length L Ch R = 1 ,4841.6  ,48.6,51.5,53.2
XS GIS Cut Line= 4
     1533618.416      222810.154     1533420.499      222763.279
     1533324.145      222765.883     1533002.096      222744.182
#Sta/Elev= 30
       0  802.89    58.1   789.2    67.8  786.77    77.5  783.51    96.8  774.88
   125.9  760.04   135.6   754.7     155   742.1   164.6  737.38     184  732.94
   203.4  727.74     213  726.13   222.7  725.48   239.7  725.23     242  725.22
   254.7  725.31   270.9  726.31   290.1  728.67   319.3  731.16     378  734.05
   426.9  738.37   446.5  739.22   456.3  740.01   466.1  741.81   475.8  744.61
   495.4  752.96   505.2   756.1   534.5   761.6   573.6  768.22   622.6  777.21
#Mann= 3 , 0 , 0
       0     .05       0   239.7    .045       0   254.7     .05       0
Bank Sta=239.7,254.7
XS Rating Curve= 0 ,0
Exp/Cntr=0.3,0.1

Type RM Length L Ch R = 1 ,4790.1  ,114.5,132.1,149.7
XS GIS Cut Line= 4
     1533632.305      222778.904     1533444.805      222719.877
     1533371.888      222719.877     1533014.249      222693.835
#Sta/Elev= 30
       0  809.31    39.3  797.84    49.1  794.49    68.8   786.6    78.6  782.05
    88.5  776.61   147.4  742.16   157.3   738.3   167.1  736.75   176.9  736.12
   186.7  734.84   214.8  729.46   223.9  726.66   231.7  724.93   242.2  724.08
   246.7  724.36   269.5  727.11   337.3  733.14   376.1  735.83   405.2  737.14
   414.9  739.38   424.6  743.69   443.9  756.81   463.3  766.88     473     771
   492.4  777.67   531.2  788.05   550.5  792.53     599  802.62   628.1  806.69
#Mann= 3 , 0 , 0
       0     .06       0   231.7    .045       0   246.7    .055       0
Bank Sta=231.7,246.7
XS Rating Curve= 0 ,0
Exp/Cntr=0.3,0.1

Type RM Length L Ch R = 1 ,4658.1  ,547.7,552.4,556.7
XS GIS Cut Line= 4
     1533723.884      222781.508      1533489.25      222635.811
     1533427.009      222578.383     1533095.412      222376.995
#Sta/Elev= 30
       0  824.71    57.1  812.94    85.7  804.39   104.8  797.16   123.8  788.36
   152.4  773.92   209.5  741.63     219  737.77   247.6  734.46   276.2   729.4
   302.7  723.69   313.8  722.96   317.7   723.3   419.1  732.35   428.8   737.3
   457.9     757   496.7  781.43   516.1  792.67   525.8  797.02   554.9  807.99
   574.3  816.07     613  835.49   622.8  839.27   632.4  842.06   642.2   844.1
   661.6  846.41     681  849.88   700.3  854.68   719.7  861.55   748.8  873.69
#Mann= 3 , 0 , 0
       0    .065       0   302.7    .045       0   317.7     .06       0
Bank Sta=302.7,317.7
XS Rating Curve= 0 ,0
Exp/Cntr=0.3,0.1

Type RM Length L Ch R = 1 ,4105.7  ,799.3,780.9,761.2
XS GIS Cut Line= 4
     1534081.089      222656.508     1533885.777      222271.092
      1533812.86      222169.529     1533448.277        221901.3
#Sta/Elev= 30
       0  815.34    58.9  812.12    78.6  809.19   127.7  796.24   186.6  783.27
     216  773.52   284.8  744.05   333.9  731.76   373.2  727.64   460.9  725.78
   483.8  721.42   499.4  718.46     509  718.14  511.83718.4437   528.2  721.95
   557.1  733.55   576.8  739.49   596.5  742.18   645.7   744.5   665.3  747.42
   753.9   767.9   763.7  772.88   783.4  785.68   812.9   796.7   852.3  820.91
   881.8  833.02   901.5  839.43   911.3  841.52     990  852.96  1009.7  861.83
#Mann= 3 , 0 , 0
       0     .06       0   483.8    .045       0  511.83      .1       0
Bank Sta=483.8,511.83
XS Rating Curve= 0 ,0
Exp/Cntr=0.3,0.1

Type RM Length L Ch R = 1 ,3324.8  ,676.2,682.7,689
XS GIS Cut Line= 4
     1534601.633      221652.602     1534232.912      221535.425
     1534091.217      221520.658     1533816.911      221503.297
#Sta/Elev= 30
       0  851.03     9.7  848.09    19.3  845.97      58  840.46   106.4  834.51
   212.8  829.57   222.5  828.51   232.1  826.24   241.8  822.08   261.2  812.01
   299.8  793.56   377.2  751.32   424.9  726.27   434.4  723.42   443.9  721.89
  457.47716.3726   462.9  713.73   472.4  711.71  476.77711.7928   529.4   716.8
   558.8  717.57   578.4  720.43   598.1  724.99     657   746.2   686.4  755.38
     706  762.43   725.7  771.15   774.8  799.27   784.6   803.2   804.2  809.66
#Mann= 3 , 0 , 0
       0     .06       0  457.47     .04       0  476.77     .05       0
Bank Sta=457.47,476.77
XS Rating Curve= 0 ,0
Exp/Cntr=0.3,0.1

Type RM Length L Ch R = 1 ,2642.1  ,167.8,166.9,165.4
XS GIS Cut Line= 4
      1534714.48      221060.371     1534439.958      220927.993
     1534296.729      220869.399     1534050.418      220815.146
#Sta/Elev= 30
       0  842.84     9.8   839.9    68.8  819.97    78.6  816.01   108.2  802.73
     118  797.87   157.3  776.99   167.1  772.03   186.8  762.62   206.5  753.91
     236  741.97   245.8  737.74   285.1  719.39   294.9   715.8   304.8  714.63
   324.1  713.85   411.2  706.98   416.3  706.84   420.8  706.72   430.5  708.37
   431.3   708.8   440.2  713.61   449.8  720.31   459.5  726.13     508  751.51
   556.5  774.61   585.6  787.88   634.1  809.27   663.2  821.15   711.7  839.95
#Mann= 3 , 0 , 0
       0     .05       0   416.3    .045       0   431.3      .1       0
Bank Sta=416.3,431.3
XS Rating Curve= 0 ,0
Exp/Cntr=0.3,0.1

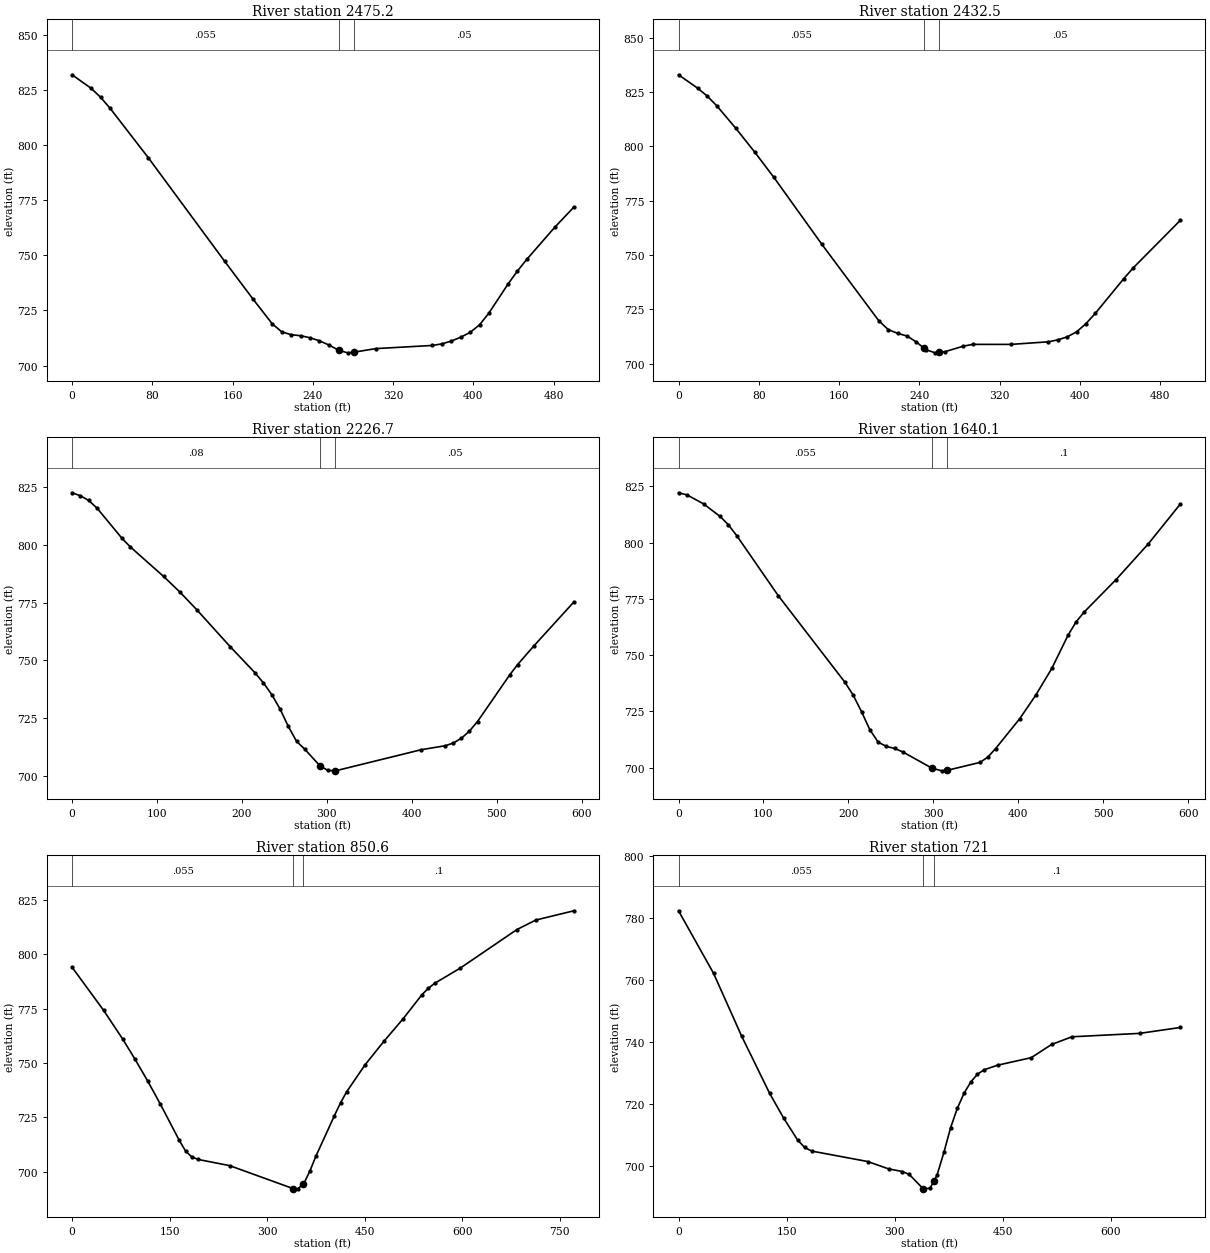
Type RM Length L Ch R = 1 ,2475.2  ,42,42.7,42.7
XS GIS Cut Line= 4
     1534709.055      220865.059     1534512.658      220793.444
     1534433.882      220763.496     1534232.493      220716.621
#Sta/Elev= 30
       0  831.82      19  825.69    28.5  821.59      38  816.58      76  794.22
     152  747.34   180.5  730.07   199.5  718.95     209  715.31   218.4  714.02
   227.8  713.57   237.1  712.65   246.5  711.27   255.9  709.37   265.6  707.01
   274.6  705.81   280.6  706.08   302.7  707.73   359.1  709.16   368.5  709.87
   377.9  711.14   387.3  712.87   396.7  715.08   406.1   718.5   415.5  723.88
   434.3  736.85   443.7   742.8   453.1  748.13   481.3  762.83   500.1  771.84
#Mann= 3 , 0 , 0
       0    .055       0   265.6    .045       0   280.6     .05       0
Bank Sta=265.6,280.6
XS Rating Curve= 0 ,0
Exp/Cntr=0.3,0.1

Type RM Length L Ch R = 1 ,2432.5  ,224.6,205.8,187
XS GIS Cut Line= 4
     1534718.821      220827.081     1534522.423      220755.467
     1534443.647      220725.519     1534242.258      220678.644
#Sta/Elev= 30
       0  832.97      19  826.82    28.5  823.21      38  818.77      57   808.4
      76  797.37      95  785.78   142.5   755.2   199.5  719.87     209  715.74
   218.4  714.01   227.8  712.79   237.1  710.02   244.2  707.36   246.5   706.5
   255.9  705.06   259.2  705.23   265.2  705.54     284  708.16   293.3  708.95
   330.9  708.94   368.5  710.13   377.9  711.01   387.3   712.4   396.7  714.72
   406.1  718.51   415.5  723.31   443.7  739.16   453.1  744.11   500.1  766.01
#Mann= 3 , 0 , 0
       0    .055       0   244.2    .045       0   259.2     .05       0
Bank Sta=244.2,259.2
XS Rating Curve= 0 ,0
Exp/Cntr=0.3,0.1

Type RM Length L Ch R = 1 ,2226.7  ,586.2,586.6,586.9
XS GIS Cut Line= 4
     1534778.066      220441.592     1534517.992      220528.237
     1534437.781      220568.532     1534220.804      220634.569
#Sta/Elev= 30
       0  822.65     9.8  821.36    19.6  819.32    29.4     816    58.7  802.93
    68.5  799.22   107.7   786.4   127.3  779.49   146.8  771.95     186     756
   215.4  744.61   225.2  740.28     235  735.21   244.8  728.96   254.6  721.35
   264.3   714.9   274.1  711.44   291.7  704.34   301.1  702.31     310  702.13
   411.1  711.29   439.5  713.03   448.9   714.2   458.4  716.28   467.8  719.37
   477.3  723.51   515.1  743.66   524.5   748.2   543.4  756.18   590.7  775.32
#Mann= 3 , 0 , 0
       0     .08       0   291.7    .045       0     310     .05       0
Bank Sta=291.7,310
XS Rating Curve= 0 ,0
Exp/Cntr=0.3,0.1

Type RM Length L Ch R = 1 ,1640.1  ,773.3,789.5,803.9
XS GIS Cut Line= 4
     1534515.045      219928.572     1534254.971      220015.216
      1534174.76      220055.511     1533957.783      220121.548
#Sta/Elev= 30
       0  822.19     9.8  821.26    29.4  817.28      49  811.65    58.7  807.95
    68.5  803.13   117.5  776.38   195.8  737.97   205.6  732.21   215.4  724.85
   225.2  716.83     235   711.3   244.8  709.37   254.6  708.48   264.3  706.89
  298.31699.7246     310  698.54   316.3  698.77   354.9  702.29   363.9  704.58
   373.3  708.46   401.7  721.76   420.6  732.24   439.5  744.15   458.4  758.75
   467.8  764.67   477.3  769.08   515.1  783.61   552.9  799.43   590.7  817.18
#Mann= 3 , 0 , 0
       0    .055       0  298.31    .045       0   316.3      .1       0
Bank Sta=298.31,316.3
XS Rating Curve= 0 ,0
Exp/Cntr=0.3,0.1

Type RM Length L Ch R = 1 ,850.6   ,118.6,129.6,139.8
XS GIS Cut Line= 4
     1534372.944      219572.669       1534178.5      219369.544
     1534013.569      219331.349     1533695.861      219378.224
#Sta/Elev= 30
       0  794.02    48.5  774.22    77.6  761.14      97  751.67   116.4  741.67
   135.8  731.12   164.8  714.49   174.5  709.58   184.2  706.84   193.9   705.7
   242.4  702.86   340.1  692.29     347   692.2   355.1  694.29   356.4  694.62
   365.8  700.47   375.2  707.38   403.5  725.88   412.9  731.79   422.3  736.83
   450.5  749.18   479.7  760.06   508.9  770.28   538.1  781.45   547.8  784.33
   557.5  786.63   596.5  793.55     684  811.34   713.2  815.72   771.6  819.97
#Mann= 3 , 0 , 0
       0    .055       0   340.1    .045       0   355.1      .1       0
Bank Sta=340.1,355.1
XS Rating Curve= 0 ,0
Exp/Cntr=0.3,0.1

Type RM Length L Ch R = 1 ,721     ,70.3,70,70.8
XS GIS Cut Line= 5
     1534379.628      219509.301      1534224.68      219285.342
     1534151.763      219222.842     1534034.454      219192.059
     1533827.545      219192.894
#Sta/Elev= 30
       0  782.33    48.6  762.18    87.5  741.99   126.4  723.54   145.9  715.53
   165.4  708.44   175.1  706.08   184.8  704.91   262.6  701.54   291.5  699.18
   310.8  698.31   320.4  697.37   339.3  692.82   339.6  692.74   349.2  692.94
   354.3  695.16   358.8  697.12   368.4   704.5   377.7  712.44     387  718.68
   396.4  723.56   405.7  727.18     415  729.68   424.4  731.12     443  732.58
   489.6     735   517.9  739.25   546.1  741.73   640.1  742.83   696.6  744.73
#Mann= 3 , 0 , 0
       0    .055       0   339.3    .045       0   354.3      .1       0
Bank Sta=339.3,354.3
XS Rating Curve= 0 ,0
Exp/Cntr=0.3,0.1

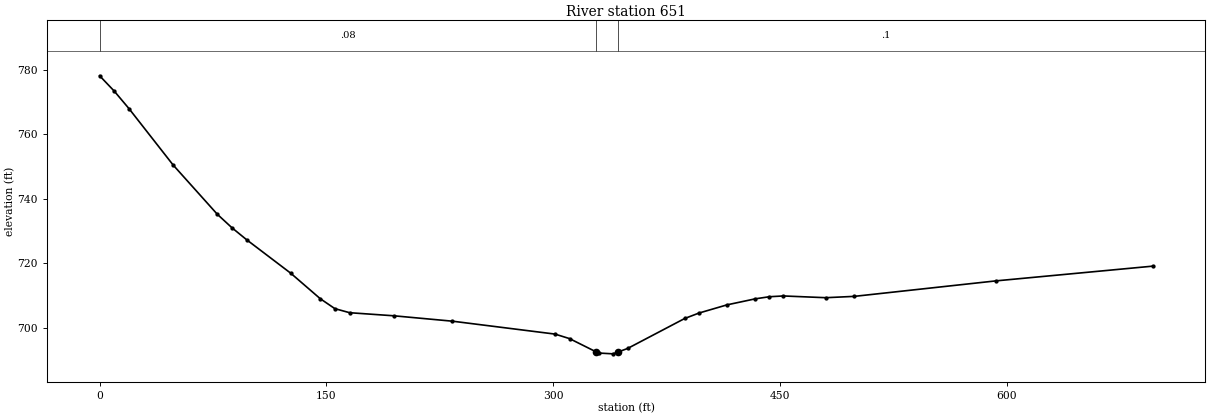
Type RM Length L Ch R = 1 ,651     ,677.3,651,617.8
XS GIS Cut Line= 5
     1534408.274      219442.894     1534253.326      219218.936
     1534180.409      219156.436     1534063.099      219125.653
     1533856.191      219126.488
#Sta/Elev= 30
       0  778.15     9.7  773.37    19.4  767.97    48.6  750.47    77.8   735.2
    87.5     731    97.3  727.25   126.4  716.89   145.9  708.99   155.6  705.89
   165.4  704.63   194.5  703.68   233.4     702   301.2     698   310.8   696.6
   328.2  692.53     330  692.12   339.6  691.87   343.2  692.49   349.2  693.53
     387  702.84   396.4  704.52     415  707.07   433.7  708.94     443  709.59
   452.3  709.83   480.3  709.29   499.1   709.7   593.1  714.52   696.6  719.08
#Mann= 3 , 0 , 0
       0     .08       0   328.2    .045       0   343.2      .1       0
Bank Sta=328.2,343.2
XS Rating Curve= 0 ,0
Exp/Cntr=0.3,0.1

Chan Stop Cuts=-1
Use User Specified Reach Order=0
Composite Channel Slope=5